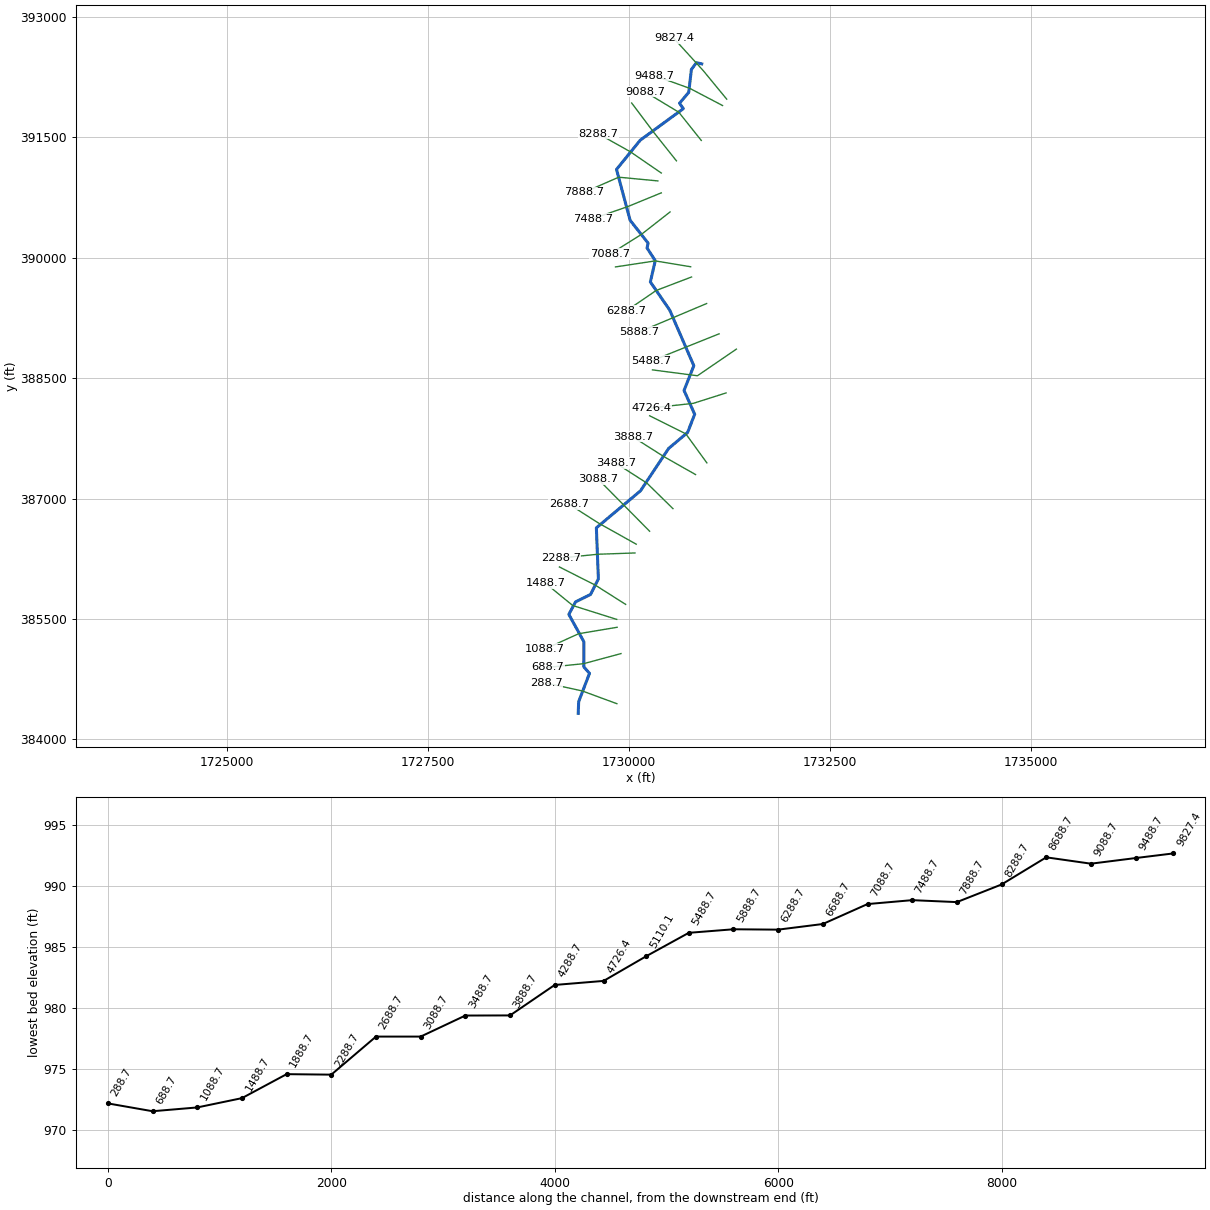
--- FltRn.prj (project) ---

Proj Title=FltRn
Current Plan=p01
Default Exp/Contr=0,0
English Units
Geom File=g01
Flow File=f01
Plan File=p01
BEGIN DESCRIPTION:
END DESCRIPTION:
DSS Export Rating Curves= 0
DSS Export Rating Curve Sorted= 0
DSS Export Volume Flow Curves= 0
DXF OffsetX= 0
DXF OffsetY= 0
DXF ScaleX= 0
DXF ScaleY= 0

--- FltRn.p01 (plan) ---

Plan Title=Floodplain
Program Version=4.00
Geom File=g01
Flow File=f01
K Sum by GR=0
Std Step Tol=0.01
Critical Tol=0.01
Num of Std Step Trials=20
Max Error Tol=0.3
Flow Tol Ratio=0.001
Split Flow NTrial=30
Split Flow Tol=0.02
Split Flow Ratio=0.02
Log Output Level=0
Friction Slope Method=1
Unsteady Friction Slope Method=2
Unsteady Bridges Friction Slope Method=1
Global Log Level=0
CheckData=False
Run HTab=0
Run UNet=0
Run PostProcess=0
UNET Theta=0
UNET Theta Warmup=0
UNET ZTol=0
UNET ZSATol=0
UNET MxIter=0
UNET MaxInSteps=0
UNET DtIC=0
UNET DtMin=0
UNET MaxCRTS=0
UNET WFStab=0
UNET SFStab=0
UNET WFX=0
UNET SFX=0
UNET DSS MLevel=0
UNET DZMax Abort=0
UNET Convert EG Bridges=0
UNET Use Existing IB Tables=0
UNET Froude Limit=0
UNET Froude Power=0
Write IC File=0
Echo Input=False
Echo Output=False
Write Detailed=0

--- FltRn.f01 (steady flow) ---

Flow Title=NFF Regression Equation
Program Version=4.00
Number of Profiles=1
Profile Names=P100yr
River Rch & RM=FltRn,Main      ,9827.4
2019.547
River Rch & RM=FltRn,Main      ,5110.1
2092.951
River Rch & RM=FltRn,Main      ,4726.4
2464.494
River Rch & RM=FltRn,Main      ,288.7
2526.958
Boundary for River Rch & Prof#=FltRn,Main      ,1
Up Type=0
Dn Type=3
Dn Slope=0.002103

--- FltRn.g01 (geometry) ---

Geom Title=USGS 3m DEM
Program Version=4.00

River Reach=FltRn     ,Main
Reach XY= 30
     1730902.742      392416.880     1730837.308      392432.040
     1730774.374      392347.404     1730741.821      392063.116
     1730626.804      391926.397     1730674.547      391859.123
     1730138.523      391466.328     1729843.384      391101.744
     1730012.655      390468.064     1730236.179      390183.776
     1730223.158      390123.012     1730325.155      389964.592
     1730264.391      389699.835     1730505.276      389348.272
     1730804.755      388655.998     1730683.228      388347.838
     1730815.606      388050.529     1730726.631      387822.665
     1730491.643      387625.052     1730141.642      387096.976
     1729592.931      386635.444     1729617.982      385998.934
     1729520.818      385805.549     1729334.086      385712.909
     1729250.649      385556.887     1729437.404      385216.104
     1729436.952      384902.674     1729507.570      384822.198
     1729372.876      384469.367     1729367.236      384323.445

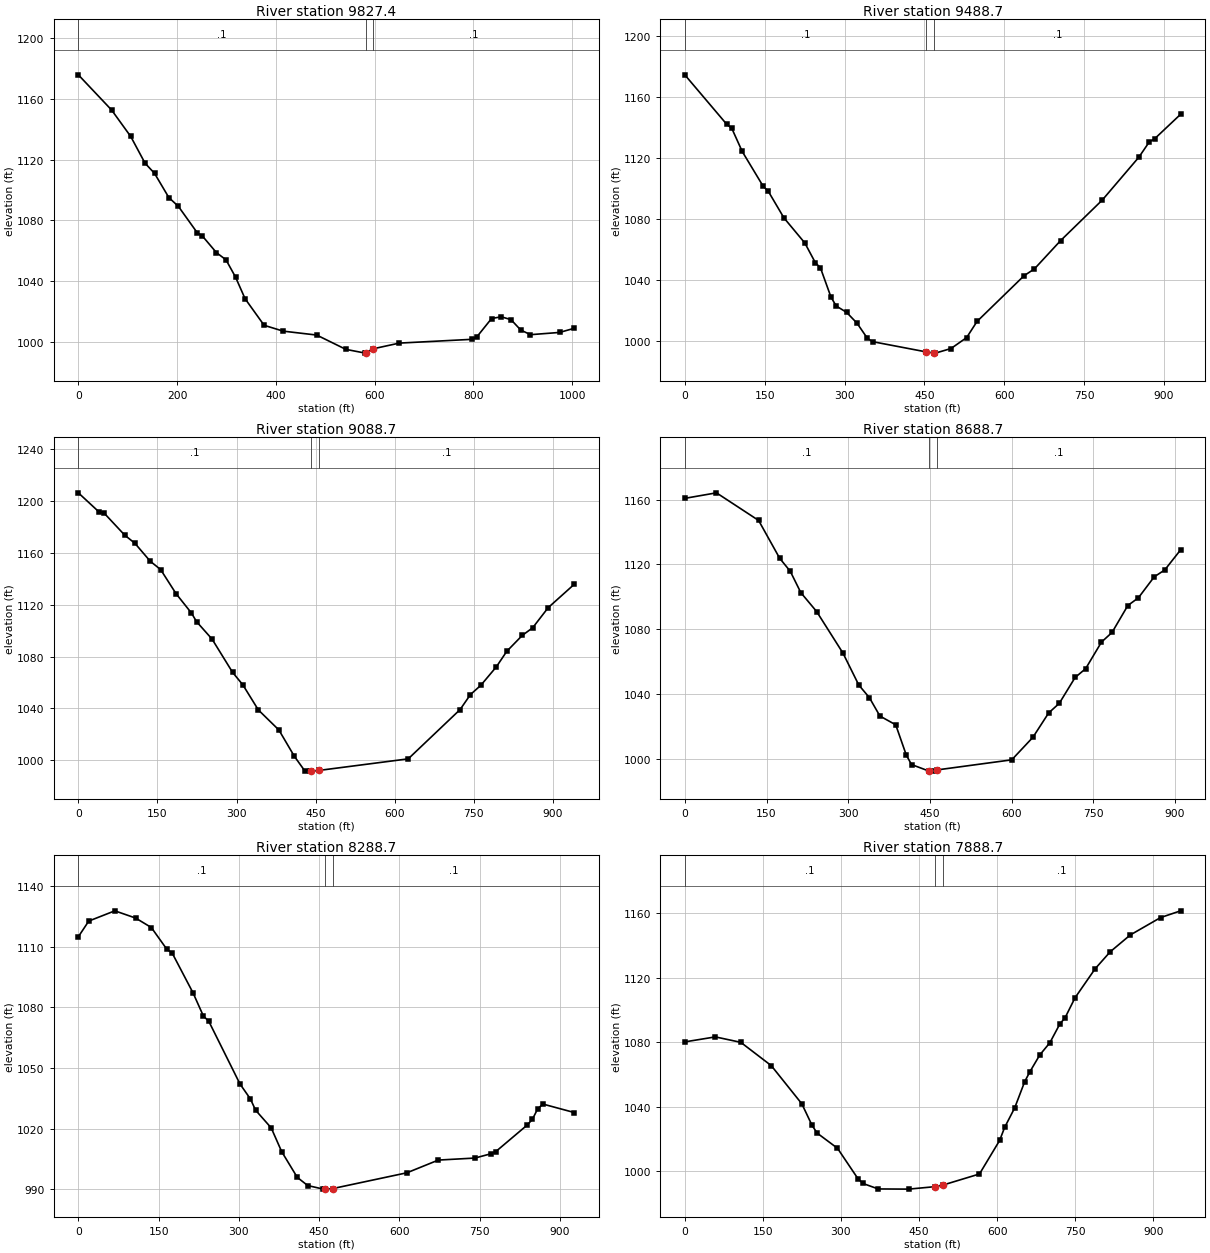
Type RM Length L Ch R = 1 ,9827.4,334.1,338.78,350.475
XS GIS Cut Line= 3
     1731213.896      391977.186     1730920.180      392335.138
     1730556.270      392735.428
#Sta/Elev= 30
       0 1175.92    67.5 1152.70   106.1 1135.32   135.1 1117.72   154.3 1111.03
   183.3 1095.09   202.6 1089.28   241.2 1071.74   250.8 1069.92   279.7 1058.82
   299.0 1054.09   318.3 1042.73   337.6 1028.49   376.2 1010.97   414.8 1007.12
   482.7 1004.54   541.7  995.12   581.1  992.64   581.8  992.71   596.8  995.48
   649.9  999.24   797.5 1001.74   807.3 1003.49   836.8 1015.44   856.5 1016.56
   876.1 1014.69   895.8 1007.87   915.5 1004.79   974.5 1006.27  1004.0 1008.98
#Mann= 3 , 0 , 0
       0     0.1       0   581.8   0.045       0   596.8     0.1       0
Bank Sta=   581.8,   596.8
Exp/Cntr=0.3,0.1

Type RM Length L Ch R = 1 ,9488.7,412.785,400,381.228
XS GIS Cut Line= 3
     1731161.943      391898.240     1730754.133      392112.361
     1730311.632      392272.123
#Sta/Elev= 30
       0 1174.85    78.4 1142.53    88.2 1139.77   107.8 1124.58   147.0 1101.84
   156.8 1098.42   186.2 1080.98   225.4 1064.53   245.0 1051.70   254.8 1048.15
   274.4 1029.12   284.2 1023.21   303.8 1019.02   323.4 1011.91   343.0 1001.92
   352.8  999.77   453.1  993.08   468.1  992.34   470.4  992.26   499.8  995.26
   529.2 1002.44   548.8 1013.05   637.0 1043.02   656.6 1047.54   705.6 1066.05
   784.0 1092.70   852.7 1120.82   872.3 1130.85   882.1 1132.83   931.1 1148.97
#Mann= 3 , 0 , 0
       0     0.1       0   453.1   0.045       0   468.1     0.1       0
Bank Sta=   453.1,   468.1
Exp/Cntr=0.3,0.1

Type RM Length L Ch R = 1 ,9088.7,400,400,391.061
XS GIS Cut Line= 3
     1730897.340      391463.222     1730618.232      391814.359
     1730197.933      392069.231
#Sta/Elev= 30
       0 1205.96    39.0 1191.32    48.8 1190.40    87.8 1173.45   107.3 1167.11
   136.5 1153.25   156.0 1146.94   185.3 1128.35   214.5 1113.44   224.3 1106.75
   253.5 1093.43   292.5 1067.79   312.0 1058.16   341.3 1038.90   380.3 1023.44
   409.5 1003.27   429.0  992.19   438.8  991.80   441.1  991.84   456.1  992.33
   625.5 1001.25   723.8 1039.16   743.5 1050.74   763.1 1057.83   792.6 1072.07
   812.3 1083.98   841.8 1096.27   861.4 1102.10   890.9 1117.61   940.1 1135.51
#Mann= 3 , 0 , 0
       0     0.1       0   441.1   0.045       0   456.1     0.1       0
Bank Sta=   441.1,   456.1
Exp/Cntr=0.3,0.1

Type RM Length L Ch R = 1 ,8688.7,392.396,400,410.486
XS GIS Cut Line= 3
     1730588.200      391209.306     1730305.102      391565.462
     1730031.803      391929.500
#Sta/Elev= 30
       0 1160.80    58.1 1164.21   135.5 1147.16   174.2 1123.78   193.6 1115.75
   213.0 1102.57   242.0 1090.90   290.4 1065.19   319.4 1045.50   338.8 1037.72
   358.2 1026.34   387.2 1020.93   406.6 1002.22   416.2  996.39   447.5  992.44
   455.0  992.32   462.5  993.04   600.2  999.30   639.0 1013.20   668.0 1028.28
   687.4 1034.17   716.5 1050.16   735.8 1055.59   764.9 1072.02   784.3 1077.98
   813.3 1094.61   832.7 1099.38   861.7 1112.32   881.1 1116.59   910.2 1129.00
#Mann= 3 , 0 , 0
       0     0.1       0   447.5   0.045       0   462.5     0.1       0
Bank Sta=   447.5,   462.5
Exp/Cntr=0.3,0.1

Type RM Length L Ch R = 1 ,8288.7,394.849,400,421.303
XS GIS Cut Line= 3
     1730400.334      391056.956     1730015.259      391322.146
     1729615.309      391547.003
#Sta/Elev= 30
       0 1114.92    19.5 1122.70    68.2 1127.76   107.1 1124.18   136.4 1119.50
   165.6 1108.66   175.3 1106.89   214.3 1087.19   233.8 1075.64   243.5 1073.25
   302.0 1042.12   321.4 1034.75   331.2 1029.15   360.4 1020.38   379.9 1008.66
   409.1  995.91   428.6  991.87   457.8  990.10   460.1  990.10   475.1  990.36
   614.0  998.19   672.6 1004.47   740.9 1005.47   770.2 1007.54   779.9 1008.65
   838.5 1021.76   848.3 1024.61   858.0 1029.66   867.8 1032.19   926.4 1028.00
#Mann= 3 , 0 , 0
       0     0.1       0   460.1   0.045       0   475.1     0.1       0
Bank Sta=   460.1,   475.1
Exp/Cntr=0.3,0.1

Type RM Length L Ch R = 1 ,7888.7,380.945,400,398.831
XS GIS Cut Line= 3
     1730357.418      390958.616     1729870.692      391005.155
     1729446.261      390818.213
#Sta/Elev= 30
       0 1080.18    58.7 1083.29   107.6 1079.90   166.2 1065.41   224.9 1041.68
   244.5 1028.30   254.3 1023.49   293.4 1014.05   332.5  995.25   342.3  992.18
   371.6  988.77   430.3  988.66   481.4  990.21   496.4  991.23   566.2  998.08
   604.9 1018.89   614.6 1027.06   633.9 1039.18   653.2 1055.56   662.9 1061.52
   682.2 1072.12   701.5 1079.68   720.8 1091.42   730.5 1095.07   749.8 1107.59
   788.5 1125.66   817.5 1136.22   856.1 1146.67   914.1 1157.45   952.7 1161.65
#Mann= 3 , 0 , 0
       0     0.1       0   481.4   0.045       0   496.4     0.1       0
Bank Sta=   481.4,   496.4
Exp/Cntr=0.3,0.1

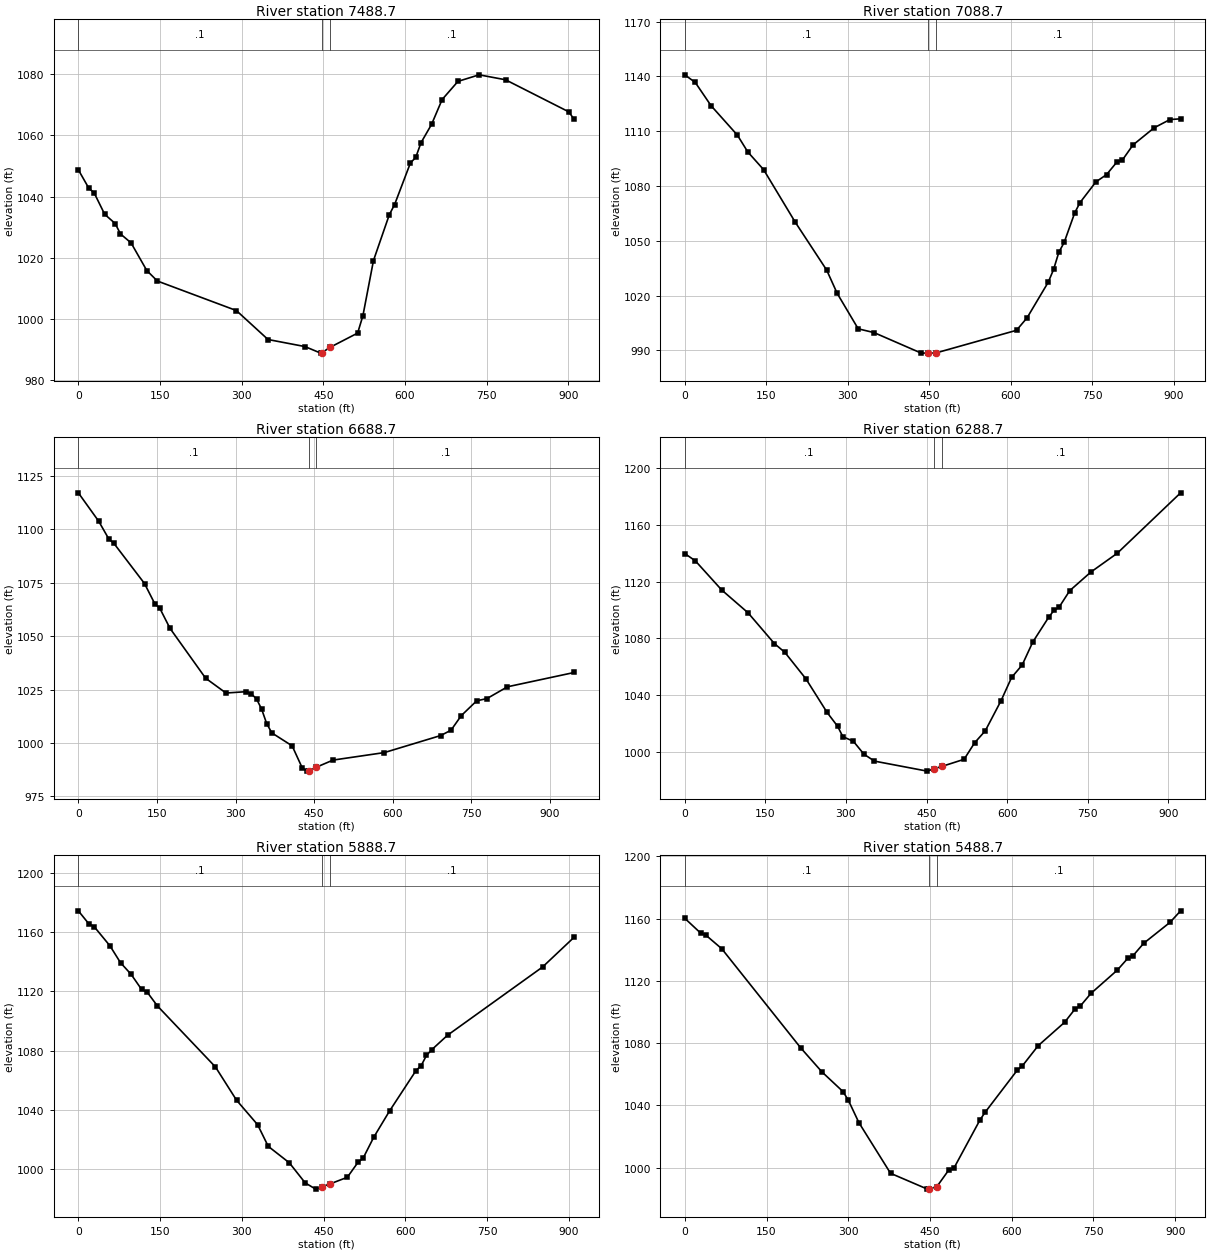
Type RM Length L Ch R = 1 ,7488.7,393.37,400,405.577
XS GIS Cut Line= 3
     1730400.141      390809.863     1729979.402      390637.059
     1729548.568      390488.011
#Sta/Elev= 30
       0 1048.73    19.4 1042.67    29.0 1041.20    48.4 1034.19    67.7 1031.16
    77.4 1027.77    96.8 1024.86   125.8 1015.80   145.2 1012.38   290.3 1002.73
   348.4  993.27   416.1  990.97   445.2  988.82   447.3  988.95   462.3  990.71
   513.0  995.37   522.7 1001.05   542.1 1019.08   571.2 1034.06   580.9 1037.37
   610.0 1050.99   619.7 1052.75   629.4 1057.58   648.8 1063.57   668.2 1071.69
   697.3 1077.62   736.1 1079.76   784.6 1078.15   901.0 1067.65   910.7 1065.17
#Mann= 3 , 0 , 0
       0     0.1       0   447.3   0.045       0   462.3     0.1       0
Bank Sta=   447.3,   462.3
Exp/Cntr=0.3,0.1

Type RM Length L Ch R = 1 ,7088.7,416.9,400,391.135
XS GIS Cut Line= 3
     1730508.984      390571.815     1730151.485      390291.198
     1729764.057      390047.028
#Sta/Elev= 30
       0 1140.91    19.3 1136.72    48.3 1124.02    96.7 1107.91   116.0 1098.65
   145.0 1089.00   203.1 1060.28   261.1 1033.97   280.4 1021.23   319.1 1001.81
   348.1  999.76   435.1  988.50     447  988.50     462  988.59   610.4 1001.00
   629.9 1007.87   668.8 1027.35   678.6 1034.31   688.3 1043.74   698.1 1049.13
   717.6 1065.39   727.3 1070.96   756.5 1082.27   776.0 1086.25   795.5 1093.28
   805.3 1094.28   824.7 1102.49   863.7 1111.91   892.9 1116.44   912.4 1116.81
#Mann= 3 , 0 , 0
       0     0.1       0     447   0.045       0     462     0.1       0
Bank Sta=     447,     462
Exp/Cntr=0.3,0.1

Type RM Length L Ch R = 1 ,6688.7,386.923,400,411.021
XS GIS Cut Line= 3
     1730765.586      389889.066     1730324.562      389961.880
     1729830.804      389886.948
#Sta/Elev= 30
       0 1117.13    38.9 1103.83    58.3 1095.48    68.0 1093.44   126.3 1074.68
   145.8 1065.29   155.5 1063.10   174.9 1053.73   242.9 1030.38   281.8 1023.43
   320.7 1024.06   330.4 1023.00   340.1 1020.67   349.8 1015.93   359.5 1009.13
   369.3 1004.77   408.1  998.70   427.6  988.26   437.3  986.87   439.5  986.93
   454.5  988.73   486.2  992.04   584.1  995.55   691.8 1003.54   711.4 1006.04
   731.0 1012.86   760.4 1019.79   779.9 1020.82   819.1 1026.35   946.4 1033.04
#Mann= 3 , 0 , 0
       0     0.1       0   439.5   0.045       0   454.5     0.1       0
Bank Sta=   439.5,   454.5
Exp/Cntr=0.3,0.1

Type RM Length L Ch R = 1 ,6288.7,399.138,400,395.461
XS GIS Cut Line= 3
     1730776.823      389761.706     1730337.158      389593.635
     1729964.098      389338.020
#Sta/Elev= 30
       0 1139.81    19.6 1134.68    68.6 1114.16   117.7 1098.05   166.7 1076.38
   186.3 1070.13   225.5 1051.44   264.8 1027.82   284.4 1018.04   294.2 1010.70
   313.8 1007.44   333.4  998.35   353.0  993.47   451.1  986.41   463.2  988.02
   478.2  989.69   519.9  994.75   539.5 1006.41   559.2 1014.78   588.7 1036.12
   608.3 1052.47   628.0 1061.26   647.7 1077.42   677.1 1094.76   687.0 1099.73
   696.8 1102.07   716.5 1113.64   755.8 1126.76   805.0 1140.04   922.9 1182.63
#Mann= 3 , 0 , 0
       0     0.1       0   463.2   0.045       0   478.2     0.1       0
Bank Sta=   463.2,   478.2
Exp/Cntr=0.3,0.1

Type RM Length L Ch R = 1 ,5888.7,400.404,400,399.596
XS GIS Cut Line= 3
     1730964.327      389430.840     1730545.187      389253.789
     1730126.047      389076.739
#Sta/Elev= 30
       0 1174.35    19.4 1165.52    29.0 1163.68    58.1 1150.69    77.4 1139.33
    96.8 1131.50   116.2 1121.23   125.9 1119.67   145.2 1110.10   251.7 1068.91
   290.4 1046.48   329.1 1029.91   348.5 1015.35   387.2 1004.23   416.3  990.69
   435.6  986.44   447.5  988.11   462.5  990.04   493.7  994.44   513.1 1004.45
   522.8 1007.43   542.1 1021.43   571.2 1039.22   619.6 1066.41   629.3 1069.89
   638.9 1076.68   648.6 1080.56   677.7 1090.38   851.9 1136.38   910.0 1156.54
#Mann= 3 , 0 , 0
       0     0.1       0   447.5   0.045       0   462.5     0.1       0
Bank Sta=   447.5,   462.5
Exp/Cntr=0.3,0.1

Type RM Length L Ch R = 1 ,5488.7,391.758,378.549,364.646
XS GIS Cut Line= 3
     1731119.280      389053.242     1730697.028      388883.747
     1730274.777      388714.251
#Sta/Elev= 30
       0 1160.25    29.0 1150.78    38.7 1149.42    67.8 1140.71   213.0 1076.85
   251.7 1061.52   290.4 1048.83   300.1 1043.34   319.5 1028.91   377.6  996.33
   445.3  986.15   447.5  986.19   462.5  987.71   484.0  998.20   493.7  999.50
   542.1 1030.86   551.8 1035.83   609.9 1062.49   619.6 1065.41   648.6 1078.38
   697.0 1093.38   716.4 1102.04   726.1 1103.95   745.4 1111.97   793.8 1126.95
   813.2 1134.61   822.9 1136.33   842.2 1144.19   890.6 1157.68   910.0 1165.07
#Mann= 3 , 0 , 0
       0     0.1       0   447.5   0.045       0   462.5     0.1       0
Bank Sta=   447.5,   462.5
Exp/Cntr=0.3,0.1

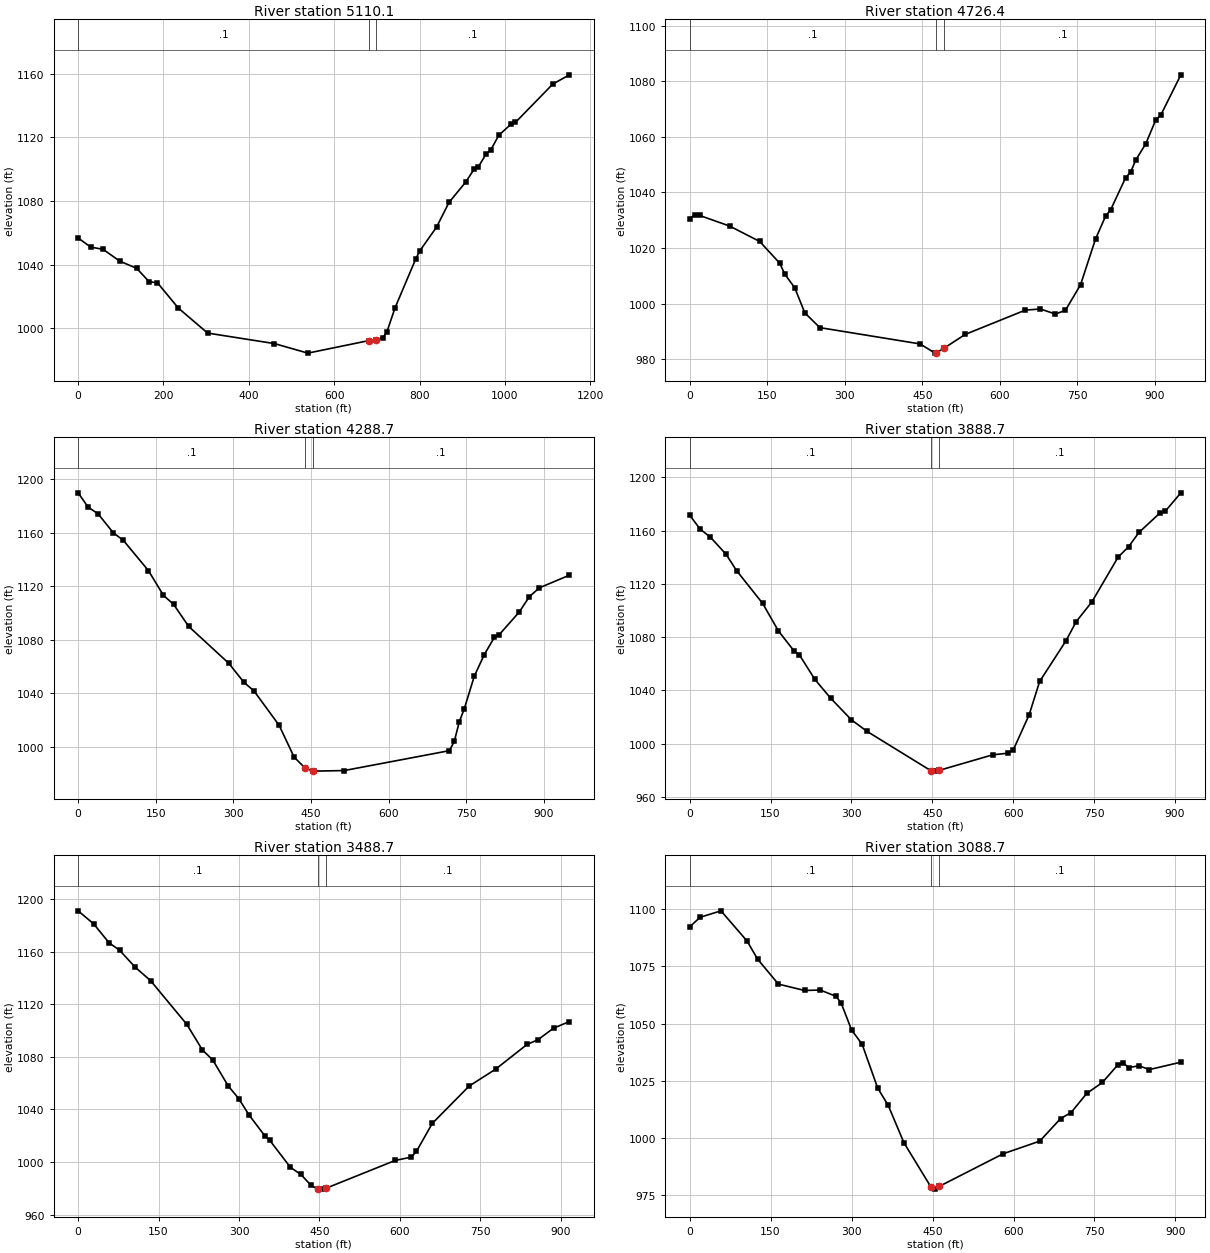
Type RM Length L Ch R = 1 ,5110.1,377.936,383.733,389.529
XS GIS Cut Line= 3
     1731334.215      388862.716     1730849.873      388530.707
     1730290.854      388603.809
#Sta/Elev= 30
       0 1056.71    29.4 1050.98    58.7 1049.53    97.9 1042.06   137.0 1037.65
   166.4 1029.21   186.0 1028.47   234.9 1012.59   303.4  996.87   460.0  990.25
   538.3  984.25   681.8  992.17   696.8  992.79   713.6  993.87   723.3  997.46
   742.7 1012.85   791.3 1043.66   801.1 1048.79   839.9 1063.56   869.1 1079.11
   908.0 1091.81   927.4 1099.80   937.1 1101.16   956.6 1109.82   966.3 1111.79
   985.7 1121.34  1014.9 1128.43  1024.6 1129.39  1112.1 1153.50  1151.0 1159.34
#Mann= 3 , 0 , 0
       0     0.1       0   681.8   0.045       0   696.8     0.1       0
Bank Sta=   681.8,   696.8
Exp/Cntr=0.3,0.1

Type RM Length L Ch R = 1 ,4726.4,462.855,437.718,423.942
XS GIS Cut Line= 3
     1731205.236      388316.373     1730799.095      388186.980
     1730278.515      388129.889
#Sta/Elev= 30
       0 1030.55     9.7 1032.00    19.4 1031.73    77.5 1027.91   135.6 1022.37
   174.4 1014.54   184.1 1010.62   203.4 1005.69   222.8  996.70   251.9  991.39
   445.7  985.53   474.7  982.22   476.8  982.31   491.8  983.96   532.9  988.94
   649.3  997.69   678.4  998.09   707.5  996.27   726.9  997.64   756.0 1006.80
   785.1 1023.32   804.5 1031.50   814.2 1033.75   843.3 1045.35   853.0 1047.35
   862.7 1051.64   882.1 1057.49   901.5 1066.08   911.2 1067.83   950.0 1082.30
#Mann= 3 , 0 , 0
       0     0.1       0   476.8   0.045       0   491.8     0.1       0
Bank Sta=   476.8,   491.8
Exp/Cntr=0.3,0.1

Type RM Length L Ch R = 1 ,4288.7,390.309,400,396.788
XS GIS Cut Line= 3
     1730966.542      387445.063     1730705.104      387807.121
     1730255.362      388031.716
#Sta/Elev= 30
       0 1189.70    19.4 1179.05    38.8 1173.95    68.0 1159.84    87.4 1154.22
   135.9 1131.62   165.0 1113.08   184.5 1106.44   213.6 1089.99   291.2 1062.39
   320.4 1048.22   339.8 1041.80   388.3 1016.21   417.5  992.31   439.1  984.00
   454.1  981.95   456.2  981.89   514.3  982.32   717.3  997.16   726.9 1004.03
   736.6 1018.76   746.3 1028.50   765.6 1052.78   784.9 1068.93   804.3 1081.70
   813.9 1083.84   852.6 1100.76   871.9 1112.11   891.3 1118.74   949.3 1128.19
#Mann= 3 , 0 , 0
       0     0.1       0   439.1   0.045       0   454.1     0.1       0
Bank Sta=   439.1,   454.1
Exp/Cntr=0.3,0.1

Type RM Length L Ch R = 1 ,3888.7,406.043,400,399.752
XS GIS Cut Line= 3
     1730826.448      387299.339     1730430.939      387523.985
     1730046.257      387768.644
#Sta/Elev= 30
       0 1171.64    19.4 1161.13    38.7 1154.99    67.7 1142.15    87.1 1129.91
   135.5 1105.28   164.5 1084.75   193.6 1069.64   203.2 1066.88   232.3 1048.25
   261.3 1034.23   300.0 1017.89   329.0 1009.23   447.4  979.71   454.9  979.40
   462.4  979.95   561.6  991.60   590.7  992.90   600.4  995.63   629.5 1021.72
   648.9 1046.70   697.4 1077.01   716.8 1091.68   745.9 1106.53   794.4 1140.05
   813.7 1147.81   833.1 1158.61   871.9 1173.16   881.6 1174.41   910.7 1188.32
#Mann= 3 , 0 , 0
       0     0.1       0   447.4   0.045       0   462.4     0.1       0
Bank Sta=   447.4,   462.4
Exp/Cntr=0.3,0.1

Type RM Length L Ch R = 1 ,3488.7,400.376,400,394.954
XS GIS Cut Line= 3
     1730545.353      386874.821     1730221.599      387192.762
     1729833.069      387442.731
#Sta/Elev= 30
       0 1191.13    29.0 1181.20    57.9 1166.72    77.2 1161.20   106.2 1148.33
   135.2 1137.95   202.7 1104.72   231.7 1085.27   251.0 1077.66   280.0 1057.80
   299.3 1048.34   318.6 1035.83   347.6 1020.19   357.2 1016.55   395.8  995.98
   415.1  990.60   434.5  982.22   446.3  979.51   453.8  979.39   461.3  979.92
   591.4 1001.26   620.9 1003.70   630.7 1008.08   660.2 1029.35   729.0 1057.81
   778.1 1070.59   837.1 1089.52   856.8 1092.93   886.3 1101.84   915.8 1106.87
#Mann= 3 , 0 , 0
       0     0.1       0   446.3   0.045       0   461.3     0.1       0
Bank Sta=   446.3,   461.3
Exp/Cntr=0.3,0.1

Type RM Length L Ch R = 1 ,3088.7,393.621,400,405.053
XS GIS Cut Line= 3
     1730255.183      386593.064     1729935.667      386917.000
     1729616.151      387240.936
#Sta/Elev= 30
       0 1092.18    19.4 1096.40    58.1 1099.23   106.5 1086.03   125.9 1078.14
   164.6 1067.21   213.0 1064.44   242.0 1064.63   271.1 1061.90   280.7 1059.00
   300.1 1047.15   319.5 1041.01   348.5 1021.77   367.9 1014.28   396.9  998.00
   447.5  978.43   455.0  977.67   462.5  978.88   580.9  993.12   648.6  998.64
   687.3 1008.50   706.7 1011.14   735.7 1019.47   764.8 1024.28   793.8 1032.10
   803.5 1032.76   813.2 1030.79   832.6 1031.52   851.9 1029.90   910.0 1033.12
#Mann= 3 , 0 , 0
       0     0.1       0   447.5   0.045       0   462.5     0.1       0
Bank Sta=   447.5,   462.5
Exp/Cntr=0.3,0.1

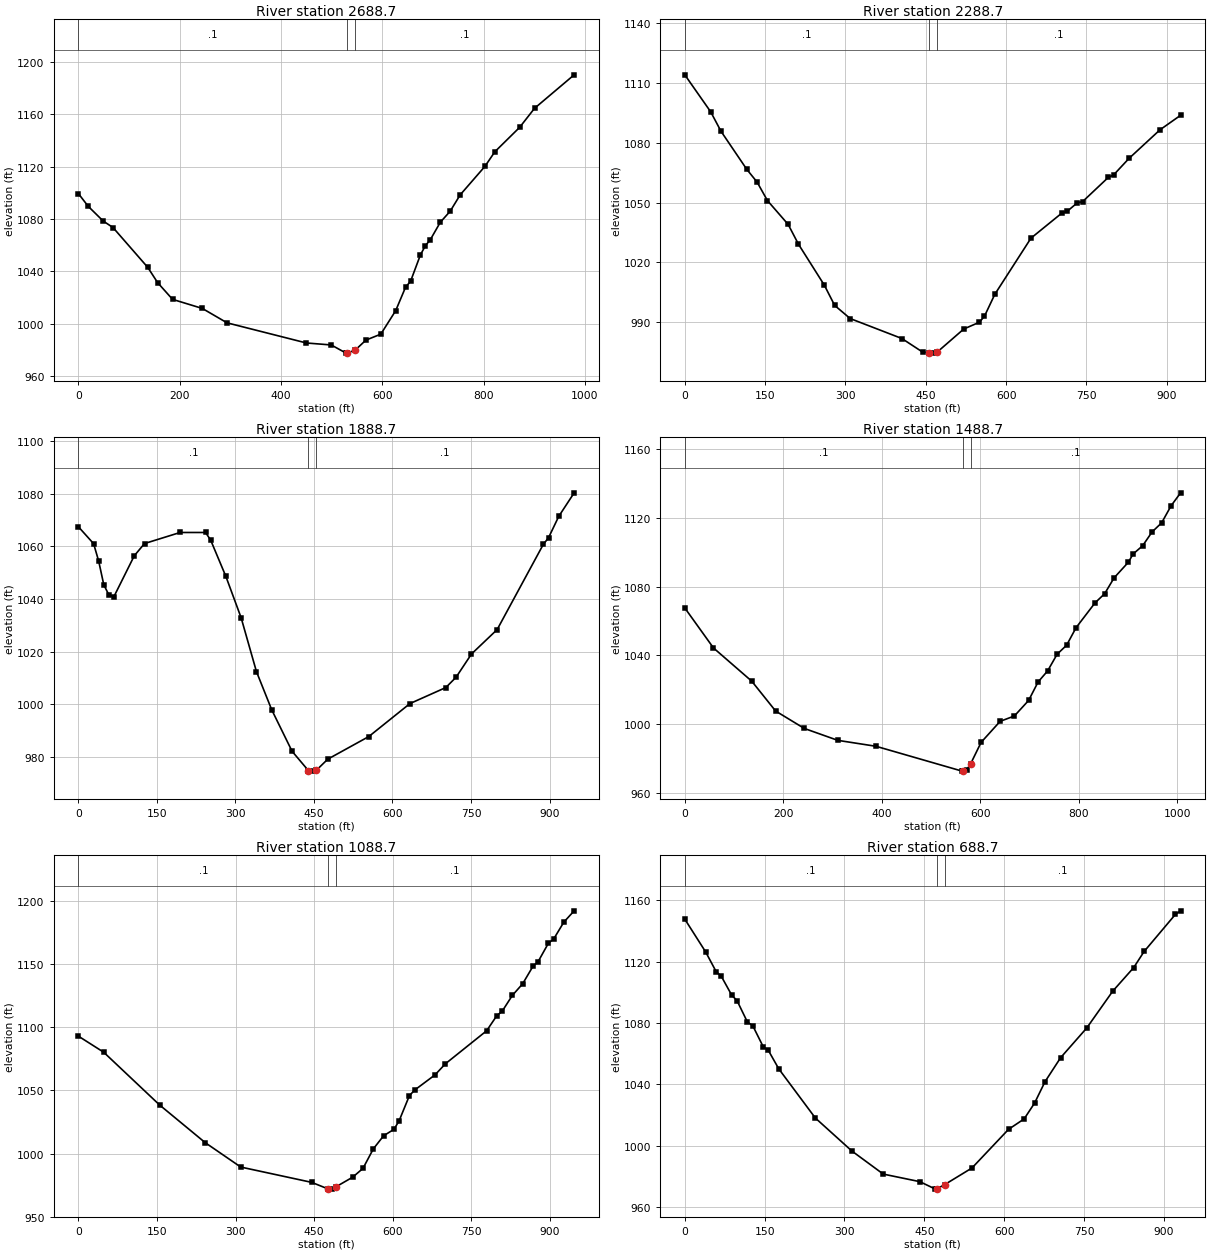
Type RM Length L Ch R = 1 ,2688.7,387.804,400,415.089
XS GIS Cut Line= 3
     1730088.743      386431.922     1729619.173      386695.178
     1729248.447      386932.710
#Sta/Elev= 30
       0 1099.49    19.6 1089.68    48.9 1078.55    68.5 1073.50   137.0 1043.14
   156.6 1031.42   186.0 1018.71   244.7 1011.78   293.6 1000.78   450.2  985.41
   499.2  983.90   528.5  977.67   530.8  977.96   545.8  979.75   567.7  987.63
   597.0  992.15   626.4 1010.11   646.0 1028.14   655.7 1032.46   675.3 1052.80
   685.1 1059.70   694.9 1064.37   714.4 1077.54   734.0 1086.03   753.6 1098.45
   802.5 1120.21   822.1 1131.38   871.0 1149.99   900.4 1164.53   978.6 1190.09
#Mann= 3 , 0 , 0
       0     0.1       0   530.8   0.045       0   545.8     0.1       0
Bank Sta=   530.8,   545.8
Exp/Cntr=0.3,0.1

Type RM Length L Ch R = 1 ,2288.7,413.46,400,387.166
XS GIS Cut Line= 3
     1730073.351      386322.470     1729610.327      386306.359
     1729149.971      386259.727
#Sta/Elev= 30
       0 1114.09    48.3 1095.57    67.6 1085.79   115.8 1066.68   135.1 1060.28
   154.4 1051.01   193.0 1039.10   212.3 1029.16   260.6 1008.63   279.9  998.48
   308.9  991.89   405.4  981.89   444.0  975.11   455.8  974.61   463.3  974.56
   470.8  974.95   521.1  986.67   550.1  990.03   559.7  993.09   579.0 1004.05
   646.5 1032.20   704.3 1044.80   713.9 1045.60   733.2 1049.97   742.9 1050.51
   791.1 1062.71   800.7 1063.87   829.6 1072.18   887.5 1086.53   926.0 1093.81
#Mann= 3 , 0 , 0
       0     0.1       0   455.8   0.045       0   470.8     0.1       0
Bank Sta=   455.8,   470.8
Exp/Cntr=0.3,0.1

Type RM Length L Ch R = 1 ,1888.7,393.764,400,395.048
XS GIS Cut Line= 3
     1729956.656      385681.675     1729579.403      385921.647
     1729133.532      386147.894
#Sta/Elev= 30
       0 1067.50    29.2 1061.04    38.9 1054.40    48.6 1045.44    58.3 1041.59
    68.0 1040.92   106.9 1056.46   126.4 1061.09   194.4 1065.30   243.0 1065.30
   252.7 1062.43   281.9 1048.57   311.0 1032.87   340.2 1012.44   369.4  997.91
   408.2  982.17   439.6  974.77   447.1  974.60   454.6  974.92   476.5  979.15
   554.9  987.75   633.4 1000.27   702.0 1006.37   721.6 1010.30   751.0 1019.12
   800.0 1028.40   888.3 1060.82   898.1 1063.28   917.7 1071.43   947.1 1080.37
#Mann= 3 , 0 , 0
       0     0.1       0   439.6   0.045       0   454.6     0.1       0
Bank Sta=   439.6,   454.6
Exp/Cntr=0.3,0.1

Type RM Length L Ch R = 1 ,1488.7,390.504,400,425.15
XS GIS Cut Line= 3
     1729845.456      385494.877     1729299.088      385667.488
     1728963.217      385942.628
#Sta/Elev= 30
       0 1067.59    58.3 1044.30   136.0 1024.98   184.5 1007.61   242.8  997.47
   310.8  990.55   388.5  987.09   563.3  972.64   565.5  972.85   573.0  973.55
   580.5  976.82   601.9  989.37   640.5 1001.60   669.5 1004.73   698.4 1013.76
   717.7 1024.53   737.0 1030.95   756.3 1040.66   775.6 1045.91   794.9 1056.15
   833.5 1070.61   852.8 1075.85   872.1 1085.12   901.0 1094.19   910.7 1099.00
   930.0 1103.77   949.3 1111.86   968.6 1117.10   987.9 1127.08  1007.2 1134.58
#Mann= 3 , 0 , 0
       0     0.1       0   565.5   0.045       0   580.5     0.1       0
Bank Sta=   565.5,   580.5
Exp/Cntr=0.3,0.1

Type RM Length L Ch R = 1 ,1088.7,397.021,400,392.666
XS GIS Cut Line= 3
     1729851.318      385396.381     1729373.807      385316.418
     1728953.332      385125.346
#Sta/Elev= 30
       0 1093.05    48.4 1080.29   154.9 1038.57   242.1 1008.68   309.9  989.36
   445.4  977.22   476.7  972.00   484.2  971.88   491.7  973.75   523.5  981.36
   543.1  988.31   562.8 1003.74   582.4 1014.11   602.1 1019.21   611.9 1025.85
   631.6 1045.86   641.4 1050.23   680.7 1062.40   700.3 1071.12   779.0 1097.28
   798.6 1109.34   808.4 1112.59   828.1 1125.30   847.7 1134.46   867.4 1148.33
   877.2 1152.01   896.9 1166.64   906.7 1169.79   926.4 1183.36   946.0 1192.26
#Mann= 3 , 0 , 0
       0     0.1       0   476.7   0.045       0   491.7     0.1       0
Bank Sta=   476.7,   491.7
Exp/Cntr=0.3,0.1

Type RM Length L Ch R = 1 ,688.7,413.43,400,393.446
XS GIS Cut Line= 3
     1729898.665      385068.337     1729434.553      384942.825
     1728986.068      384896.777
#Sta/Elev= 30
       0 1147.75    39.2 1126.35    58.9 1113.50    68.7 1110.38    88.3 1098.08
    98.1 1094.60   117.7 1080.56   127.6 1078.27   147.2 1064.58   157.0 1062.09
   176.6 1050.04   245.3 1017.97   314.0  996.42   372.9  981.38   441.5  976.45
   471.0  971.57   473.3  971.70   488.3  974.52   539.6  985.38   608.2 1010.56
   637.6 1017.40   657.2 1027.72   676.8 1041.68   706.2 1057.38   755.2 1076.73
   804.2 1100.82   843.4 1116.13   863.0 1126.64   921.8 1150.86   931.6 1153.18
#Mann= 3 , 0 , 0
       0     0.1       0   473.3   0.045       0   488.3     0.1       0
Bank Sta=   473.3,   488.3
Exp/Cntr=0.3,0.1

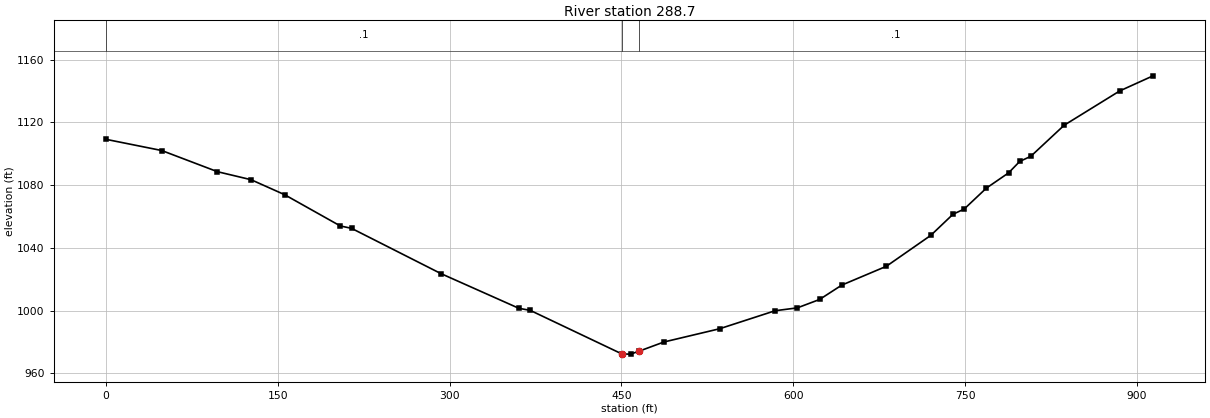
Type RM Length L Ch R = 1 ,288.7,283.777,288.67,290.342
XS GIS Cut Line= 3
     1729847.715      384444.113     1729418.112      384602.810
     1728972.672      384700.625
#Sta/Elev= 30
       0 1109.15    48.7 1102.01    97.4 1088.50   126.7 1083.40   155.9 1073.88
   204.6 1053.92   214.4 1052.40   292.3 1023.59   360.5 1001.41   370.3 1000.13
   450.5  972.29   458.0  972.21   465.5  974.12   487.1  979.95   535.6  988.37
   584.1  999.87   603.5 1001.70   622.9 1007.04   642.3 1016.21   681.2 1028.20
   720.0 1047.92   739.4 1061.39   749.1 1064.67   768.5 1078.03   787.9 1087.76
   797.6 1095.04   807.3 1098.32   836.4 1118.12   884.9 1139.99   914.0 1149.62
#Mann= 3 , 0 , 0
       0     0.1       0   450.5   0.045       0   465.5     0.1       0
Bank Sta=   450.5,   465.5
Exp/Cntr=0.3,0.1